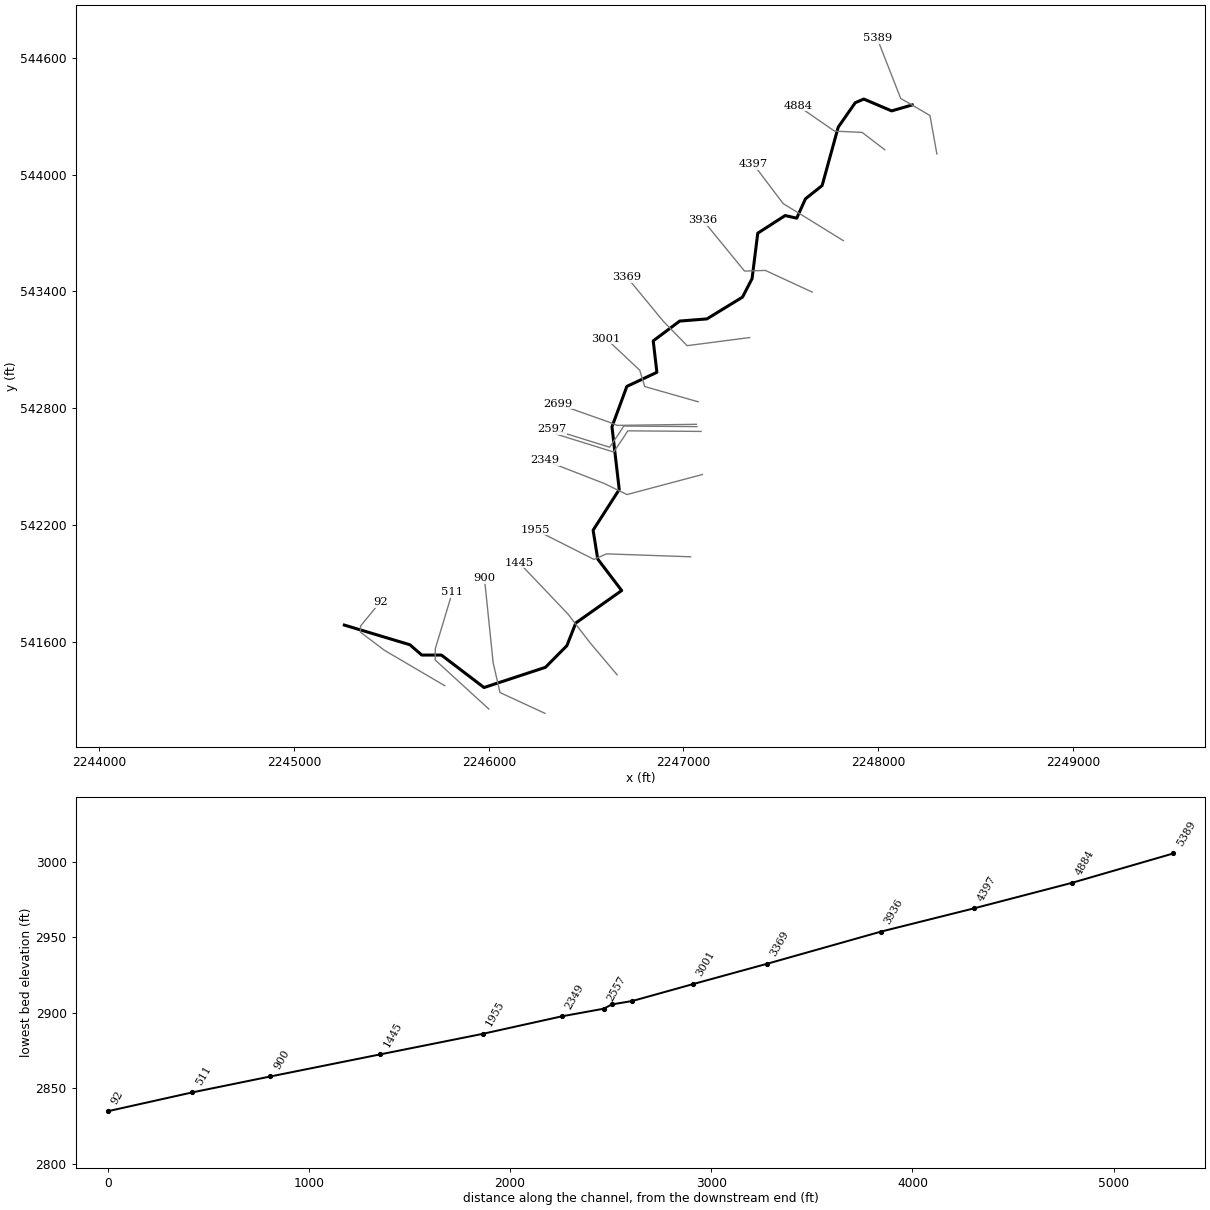
--- TYGVRV2T6.prj (project) ---

Proj Title=TYGVRV2T6
Current Plan=p01
Default Exp/Contr=0,0
English Units
Geom File=g01
Flow File=f01
Plan File=p01
BEGIN DESCRIPTION:
----------MODEL BY WOOD PLC 2022----------
AFH study
Randolph County, WV
HEC-RAS Version: RAS 6.2
Vertical Datum: NAVD88
Projection: NAD 1983 StatePlane West Virginia S FIPS 4702 (US Feet)
Terrain: 1-meter LIDAR (FEMA Region III 3DEP collected 2016-2018)
Land Use: 2019 NLCD
Hydrologic Method:
WV SIR2010-5033 regression equations
Additional Model Notes:
None
END DESCRIPTION:
DSS Export Rating Curves= 0
DSS Export Rating Curve Sorted= 0
DSS Export Volume Flow Curves= 0
DXF OffsetX= 0
DXF OffsetY= 0
DXF ScaleX= 0
DXF ScaleY= 0

--- TYGVRV2T6.p01 (plan) ---

Plan Title=Floodplain
Program Version=6.20
Short Identifier=Floodplain
Geom File=g01
Flow File=f01
Subcritical Flow
K Sum by GR= 0
Std Step Tol= 0.01
Critical Tol= 0.01
Num of Std Step Trials= 20
Max Error Tol= 0.3
Flow Tol Ratio= 0.001
Split Flow NTrial= 30
Split Flow Tol= 0.02
Split Flow Ratio= 0.02
Log Output Level= 0
Friction Slope Method= 1
Unsteady Friction Slope Method= 2
Unsteady Bridges Friction Slope Method= 1
Parabolic Critical Depth
Global Vel Dist= 0 , 0 , 0
Global Log Level= 0
CheckData=True
Encroach Param=-1 ,0,0, 0
Mapping Interval=1HOUR
Computation Time Step Use Courant=        0
Computation Time Step Use Time Series=    0
Computation Time Step Count To Double=0
Computation Time Step Max Doubling=0
Computation Time Step Max Halving=0
Computation Time Step Residence Courant=0
Run HTab= 0
Run UNet= 0
Run Sediment= 0
Run PostProcess= 0
Run WQNet= 0
Run RASMapper=-1
UNET Theta= 0
UNET Theta Warmup= 0
UNET ZTol= 0
UNET ZSATol= 0
UNET MxIter= 0
UNET Max Iter WO Improvement= 0
UNET MaxInSteps= 0
UNET DtIC= 0
UNET DtMin= 0
UNET MaxCRTS= 0
UNET WFStab= 0
UNET SFStab= 0
UNET WFX= 1
UNET SFX= 1
UNET Gravity=32.174
UNET 1D Methodology=Finite Difference
UNET DSS MLevel= 1
UNET Pardiso=0
UNET DZMax Abort= 0
UNET Use Existing IB Tables= 0
UNET Froude Reduction=False
UNET Froude Limit= 0
UNET Froude Power= 0
UNET D1 Cores= 0
UNET WindReference=Eulerian
UNET WindDragFormulation=Hsu (1988)
UNET D2 Coriolis=0
UNET D2 Cores= 0
UNET D2 Theta= 1
UNET D2 Theta Warmup= 1
UNET D2 Z Tol= 0.01
UNET D2 Volume Tol= 0.01
UNET D2 Max Iterations= 20
UNET D2 Equation= 0
UNET D2 RampUpFraction=0.1
UNET D2 TimeSlices= 1
UNET D2 Turbulence Formulation=Non-Conservative (original)
UNET D2 Eddy Viscosity=0.3
UNET D2 Transverse Eddy Viscosity=0.1
UNET D2 Smagorinsky Mixing=0
UNET D2 BCVolumeCheck=0
UNET D2 Cores=0
UNET D2 SolverType=PARDISO (Direct)
UNET D2 Minimum Iterations= 2147483647
UNET D2 Maximum Iterations= 2147483647
UNET D2 Restart Number= 10
UNET D2 Relaxation Coeff=1.3
UNET D2 SOR Precondition Iterations= 10
UNET D2 ILUT Maximum Fill= 8
UNET D2 ILUT Tolerance=1E-08
UNET D1D2 MaxIter= 0
UNET D1D2 ZTol=0.01
UNET D1D2 QTol=0.1
UNET D1D2 MinQTol=1
Write IC File= 0
Write IC File at Fixed DateTime=0
Write IC File at Sim End=0
Echo Input=False
Echo Parameters=False
Echo Output=False
Write Detailed= 0
HDF Write Warmup=0
HDF Write Time Slices=0
HDF Flush=0
HDF Compression= 1
HDF Chunk Size= 1
HDF Spatial Parts= 1
HDF Use Max Rows=0
HDF Fixed Rows= 1
Calibration Method= 0
Calibration Iterations= 20
Calibration Max Change=0.05
Calibration Tolerance=0.2
Calibration Maximum=1.5
Calibration Minimum=0.5
Calibration Optimization Method= 1
WQ AD Non Conservative
WQ ULTIMATE=-1
WQ Max Comp Step=1HOUR
WQ Output Interval=15MIN
WQ Output Selected Increments= 0
WQ Output face flow=0
WQ Output face velocity=0
WQ Output face area=0
WQ Output face dispersion=0
WQ Output cell volume=0
WQ Output cell surface area=0
WQ Output cell continuity=0
WQ Output cumulative cell continuity=0
WQ Output face conc=0
WQ Output face dconc_dx=0
WQ Output face courant=0
WQ Output face peclet=0
WQ Output face adv mass=0
WQ Output face disp mass=0
WQ Output cell mass=0
WQ Output cell source sink temp=0
WQ Output nsm pathways=0
WQ Output nsm derived pathways=0
WQ Create Restart=0
WQ Fixed Restart=0
WQ System Summary=0
WQ Write To DSS=0
Sorting and Armoring Iterations= 10
XS Update Threshold= 0.02
Bed Roughness Predictor= 0
Hydraulics Update Threshold= 0.02
Energy Slope Method= 1
Volume Change Method= 1
Sediment Retention Method= 0
Sediment TS Multiplier= 1
Warm Up Method= 0
XS Weighting Method= 0
Number of US Weighted Cross Sections= 1
Number of DS Weighted Cross Sections= 1
Upstream XS Weight=0
Main XS Weight=1
Downstream XS Weight=0
Number of DS XS's Weighted with US Boundary= 1
Upstream Boundary Weight= 1
Weight of XSs Associated with US Boundary= 0
Number of US XS's Weighted with DS Boundary= 1
Downstream Boundary Weight= 0.5
Weight of XSs Associated with DS Boundary= 0.5
Percentile Method= 0
Sediment Output Level= 3
Mass or Volume Output= 0
Output Increment Type= 1
Profile and TS Output Increment= 1
Transport Output Increment 1
XS Output Flag= 0
XS Output Increment= 10
Read HDF5 Sediment Hotstart= 0
Sediment Hotstart Type= 0
Write Gradation File= 0
Read Gradation Hotstart= 0
Write HDF5 File= 1
Write Binary Output= 1
Write DSS Sediment File= 0
DSS Sediment Output Type= 1
SV Curve= 0
Specific Gage Flag= 0
Subcell Erosion Methods= 0
Subcell Deposition Methods= 0
Advection Scheme= 1
Matrix Solver= 0
Implicit Weighting Factor= 1
Maximum Outer Loop Convergence Iterations= 5
Convergence Maximum Absolute= 0.001
Convergence RMSE= 0.0001
Grain Fractions Max Abs Error= 0.001
Max Subgrid Regions= 1
Max Subgrid Length Scale= 3.402823E+38
Initial Layer Thickness= 3.402823E+38
Min Layer Thickness= 3.402823E+38
Max Layer Thickness= 3.402823E+38
Number of Layers= 5

--- TYGVRV2T6.f01 (steady flow) ---

Flow Title=Flow
Program Version=6.20
Number of Profiles= 1
Profile Names=P100yr
River Rch & RM=TYGVRV2T6,Main,5389
     533
River Rch & RM=TYGVRV2T6,Main,511
     632
Boundary for River Rch & Prof#=TYGVRV2T6,Main            , 1
Up Type= 0
Dn Type= 3
Dn Slope=0.02803
DSS Import GetInterval= 0
DSS Import GetPeak= 0
DSS Import FillOption= 0

--- TYGVRV2T6.g01 (geometry) ---

Geom Title=Geometry
Program Version=6.20

River Reach=TYGVRV2T6       ,Main
Reach XY= 30
     2248174.548      544357.293     2248068.871      544326.698
     2247926.172      544387.492     2247882.118      544368.782
     2247794.618      544243.087     2247711.979      543943.087
     2247626.537      543875.3652247581.50593184543775.738881312
     2247522.127      543789.268     2247381.423      543698.643
     2247352.257      543465.309     2247302.951      543370.171
     2247120.316       543258.43     2246980.571      543247.296
     2246844.532      543145.609     2246863.368      542984.059
     2246709.201      542911.837     2246632.668      542704.258
     2246669.978      542382.036     2246535.837      542173.301
 2246559.5931595542025.003612659     2246682.554      541863.339
      2246446.98      541696.7642246401.09325408541580.107410224
     2246291.009      541468.976     2245975.564      541365.179
     2245756.658      541531.954     2245656.011      541531.969
     2245594.813      541584.921     2245258.081      541685.988

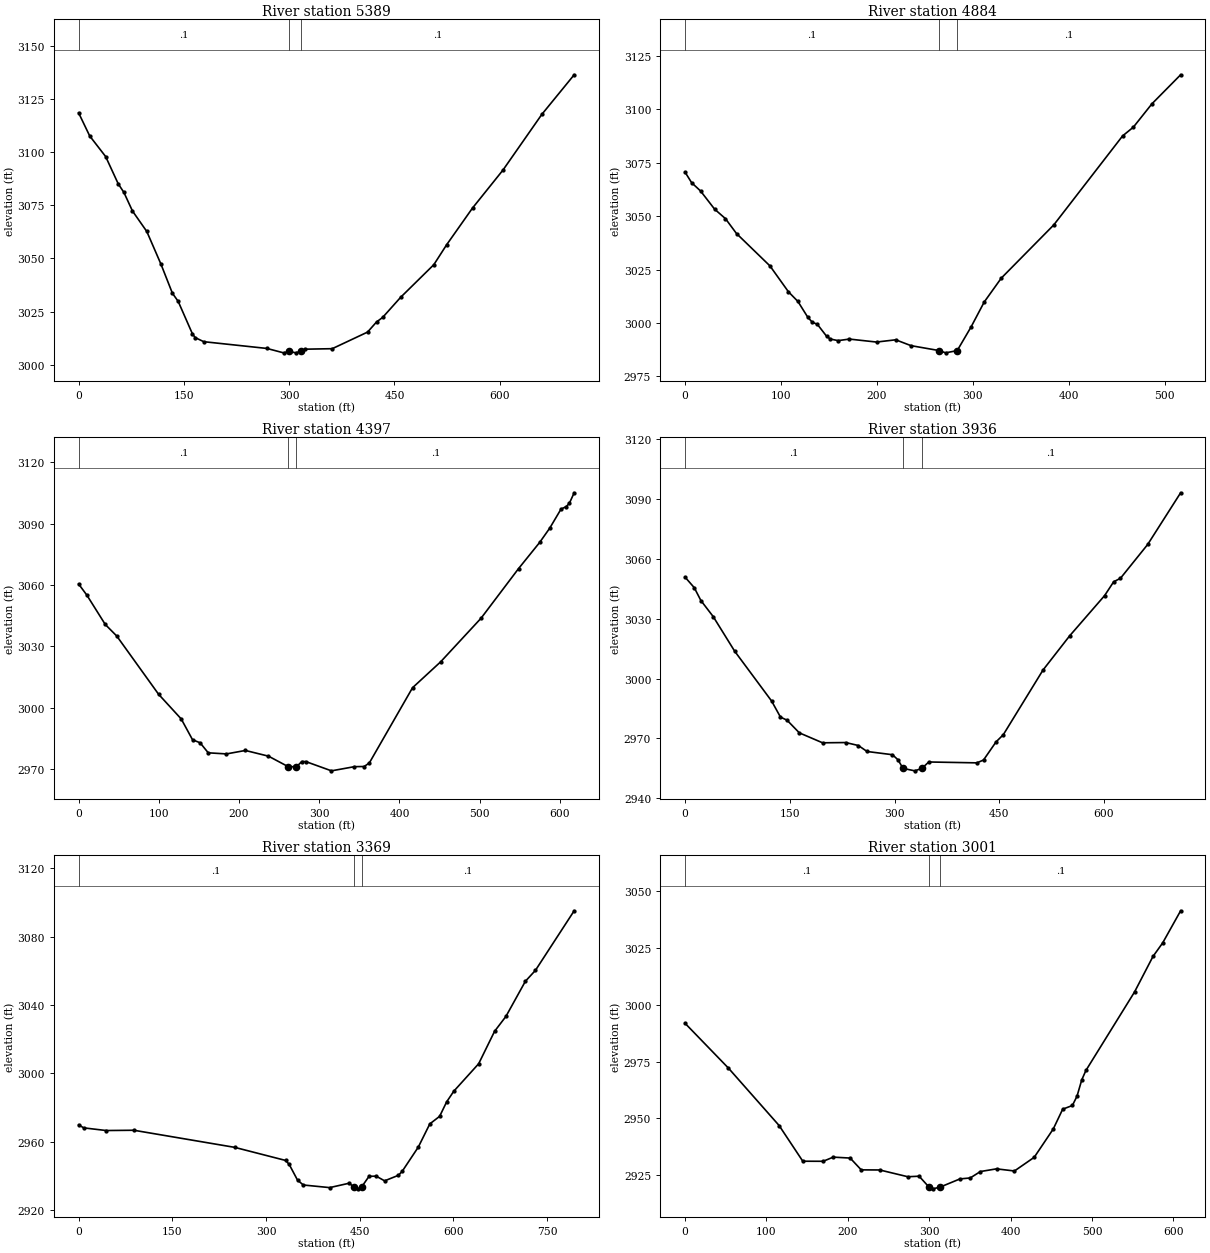
Type RM Length L Ch R = 1 ,5389    ,499,505.1,508.7
XS GIS Cut Line= 4
  2248301.391025544105.6734436532248265.79903963544303.200674229
2248115.48566928544390.8272026752247994.78576179544699.379195483
#Sta/Elev= 30
       0  3118.4    15.8 3107.55    38.5 3097.87    56.4 3085.06    64.5 3081.02
    76.7 3072.28    97.1 3062.66   117.4  3047.2   133.6 3033.61   141.8 3029.81
   162.1 3014.54   166.1 3012.74   178.3 3010.83   268.2 3007.66     292 3005.59
   299.9 3006.27   309.1 3005.62  316.893006.265     323 3007.31   361.3 3007.54
   411.6 3015.34   424.5 3020.13   433.1 3022.23   458.8 3031.71   506.1 3047.06
   524.2 3056.36   561.2 3073.69   604.5  3091.5     660 3117.74     706 3136.33
#Mann= 3 ,-1,0
       0      .1       0   299.9    .045       0  316.89      .1       0
Bank Sta=299.9,316.89
XS Rating Curve= 0 ,0
Exp/Cntr=0.3,0.1

Type RM Length L Ch R = 1 ,4884    ,490.9,487.4,481.9
XS GIS Cut Line= 4
2248033.56690746544127.3813630752247917.39665628544216.345655005
2247775.79180765544222.8827532562247587.62151583544352.665584459
#Sta/Elev= 30
       0 3070.61     6.8 3065.71    16.1 3061.83    30.8  3053.3    42.1 3048.87
    53.6 3041.91    88.5 3026.74   107.8 3014.61   117.6 3010.14   127.8 3002.81
   132.7 3000.33   137.8 2999.47   147.5 2993.85   151.5 2992.51   159.6 2991.78
   171.3  2992.5   199.6 2991.11   219.6 2992.16   235.6 2989.42  265.062987.106
   271.7 2986.06  283.722987.105   298.1 2998.11   311.9 3009.86   329.7 3021.04
   384.4 3045.93   456.2 3087.61   467.4  3091.7   486.8 3102.64   516.7 3116.22
#Mann= 3 ,-1,0
       0      .1       0  265.06    .045       0  283.72      .1       0
Bank Sta=265.06,283.72
XS Rating Curve= 0 ,0
Exp/Cntr=0.3,0.1

Type RM Length L Ch R = 1 ,4397    ,447.2,461.1,467.2
XS GIS Cut Line= 4
2247820.97492582543660.2274811442247604.89698273 543793.79494654
2247512.37748483543850.197827238 2247358.2878707544053.881242851
#Sta/Elev= 30
       0 3060.45    10.3 3054.99    33.2 3040.68    47.5 3035.04    99.7 3006.55
   127.9  2994.5     142 2984.33   151.4 2982.85   161.6 2977.94   184.3  2977.4
   207.9 2979.09   236.7  2976.3  261.382971.151   271.6 2971.15   278.3 2973.68
   283.2 2973.66   315.2 2969.13   343.9 2971.17     356 2971.25   362.4 2972.97
   416.3 3009.76   451.4 3022.44   501.7 3043.73   548.4 3067.96   574.9 3080.84
   587.4  3087.8   601.4 3097.08     608  3098.3   611.9    3100   617.8 3105.05
#Mann= 3 ,-1,0
       0      .1       0  261.38    .045       0   271.6      .1       0
Bank Sta=261.38,271.6
XS Rating Curve= 0 ,0
Exp/Cntr=0.3,0.1

Type RM Length L Ch R = 1 ,3936    ,580.7,566.6,554.7
XS GIS Cut Line= 4
 2247660.6392528543396.294464567 2247420.6489977543507.403405148
2247313.42213601543504.1587053322247099.43906522543765.754182909
#Sta/Elev= 30
       0 3050.81    13.1 3045.57    22.6 3039.12    40.2 3031.09      71 3013.72
   123.9 2988.74   136.6 2980.68     146 2979.14   163.6 2972.79   196.9  2967.8
     230 2967.93   248.1 2966.45   260.6 2963.45     297 2961.83     305 2959.25
  312.062954.978     329 2953.75  339.072954.975     349 2958.19   417.9 2957.75
   427.4 2959.18   445.4 2968.29   455.7 2971.85   512.6 3004.28   550.6 3021.35
   600.8 3041.58   613.8 3048.52   623.5 3050.26   662.5 3067.21   709.7 3093.12
#Mann= 3 ,-1,0
       0      .1       0  312.06    .045       0  339.07      .1       0
Bank Sta=312.06,339.07
XS Rating Curve= 0 ,0
Exp/Cntr=0.3,0.1

Type RM Length L Ch R = 1 ,3369    ,373.6,368.3,366.7
XS GIS Cut Line= 4
2247339.85995649543162.6208176542247018.68772564543120.998967142
2246897.00212048543245.7078795242246709.06793456543473.402239507
#Sta/Elev= 30
       0  2969.9     8.1 2968.12    44.1 2966.56    88.4 2966.72   249.8 2956.71
   331.4 2949.04   337.1 2946.71   350.4 2937.54   359.7 2934.67   401.9 2933.14
   433.3 2935.73  440.382933.473   447.1 2932.42  452.922933.459   464.9 2939.75
   476.4 2939.85   489.8  2937.1     512 2940.35   518.2 2942.79   543.8 2956.88
   562.2 2970.44   577.9 2974.87   589.2 2983.37   600.6 2989.58   640.4 3005.66
   665.9 3024.66   684.1  3033.4   715.2 3053.95   731.3 3060.34   793.3 3095.22
#Mann= 3 ,-1,0
       0      .1       0  440.38    .045       0  452.92      .1       0
Bank Sta=440.38,452.92
XS Rating Curve= 0 ,0
Exp/Cntr=0.3,0.1

Type RM Length L Ch R = 1 ,3001    ,292.9,301.7,305.5
XS GIS Cut Line= 4
 2247075.2349158 542832.773912012246800.91648148542911.028788178
2246775.13763292542994.9904323482246603.27864251543156.354217238
#Sta/Elev= 30
       0 2991.81    53.1 2972.15   115.5 2946.82   144.6  2931.1   169.6 2931.07
     182  2932.9   202.8 2932.49   216.4 2927.29   239.1 2927.25   273.6 2924.27
   287.5  2924.5  299.482919.781   304.2 2918.94   313.2 2919.69   337.7 2923.31
   350.3 2923.73   362.8 2926.56   382.6 2927.74   404.6  2926.8   428.9 2932.82
   452.3 2945.29   463.9 2954.01   475.8 2955.64   481.5 2959.74   487.3  2966.9
   492.4 2971.05   552.2 3005.64   574.8 3021.25   586.7 3027.21   608.8 3041.37
#Mann= 3 ,-1,0
       0      .1       0  299.48    .045       0   313.2      .1       0
Bank Sta=299.48,313.2
XS Rating Curve= 0 ,0
Exp/Cntr(USF)=0,0
Exp/Cntr=0.3,0.1

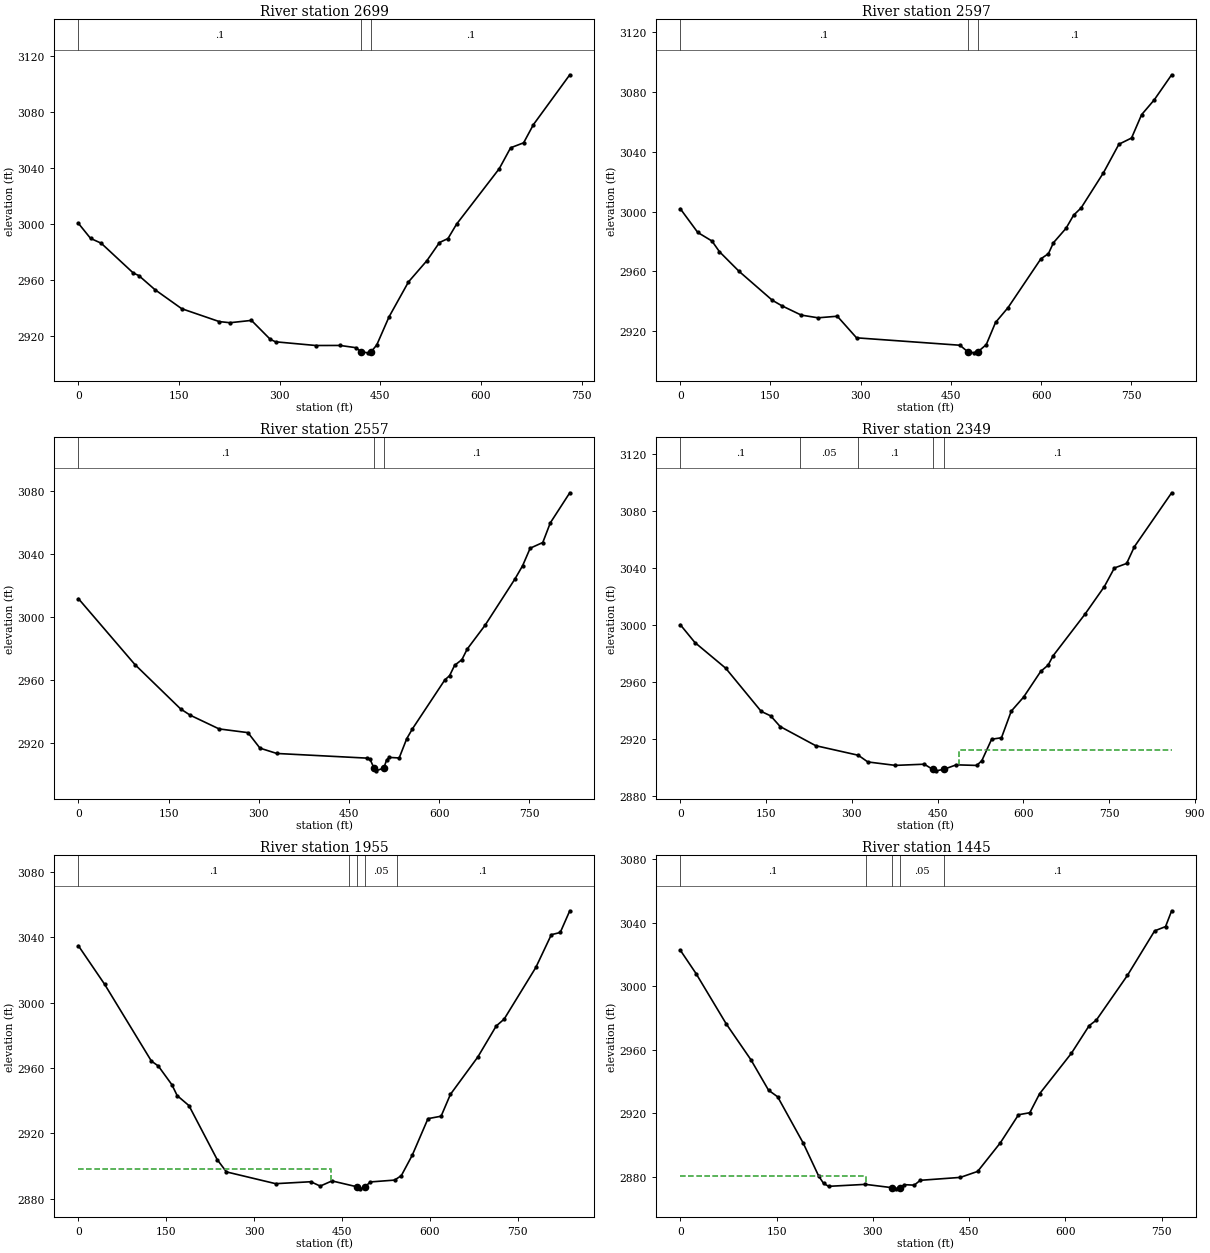
Type RM Length L Ch R = 1 ,2699    ,95.7,101.9,115.8
XS GIS Cut Line= 4
 2247066.0284323542717.1447119732246659.44522539542711.477578456
2246615.24343259542729.0953849012246353.07929575 542821.83418823
#Sta/Elev= 30
       0 3000.41    18.1 2989.65    33.9 2986.21    81.9  2964.8    89.9 2963.08
   113.9 2953.01   153.9 2939.33   209.9  2930.1   225.9 2929.29   257.9 2930.95
   285.9  2917.4   293.8 2915.63   353.9 2912.98   389.9 2913.02   413.5 2911.42
   421.5 2908.45   431.7 2907.73  436.312908.528   444.6 2913.36   462.9 2933.46
   491.9  2958.5   519.4 2973.74   538.1 2986.68   550.8 2989.55   563.5  2999.8
   627.2 3039.56   644.1  3054.5   663.5 3058.06   678.1 3071.08   732.3 3106.76
#Mann= 3 ,-1,0
       0      .1       0   421.5    .045       0  436.31      .1       0
Bank Sta=421.5,436.31
XS Rating Curve= 0 ,0
Exp/Cntr=0.3,0.1

Type RM Length L Ch R = 1 ,2597    ,38.3,40.1,36.7
XS GIS Cut Line= 6
2247069.25348029542705.1364534922246692.88816013 542708.21963476
2246674.14623168542678.232549237 2246652.1914012  542645.8357872
2246620.52821792542599.4137871462246324.46591513542691.466772048
#Sta/Elev= 30
       0 3001.87    29.1 2985.99    52.7 2980.26    65.1 2973.14    97.8 2959.97
   153.1 2940.62   169.1 2936.92   201.1 2930.73   229.1 2928.91   261.1 2929.97
   293.1 2915.52   465.1 2910.56  477.692906.288   488.8 2905.48  495.212906.286
   508.8 2910.96   524.2 2925.78   545.1 2935.77   599.6 2968.34   612.2 2971.81
   620.5 2979.11   641.5  2988.8     654 2997.52   666.6 3002.44   703.7 3025.93
   729.4 3045.01   750.4 3049.17   767.1 3064.76   788.1 3074.66   817.1 3091.46
#Mann= 3 ,-1,0
       0      .1       0  477.69    .045       0  495.21      .1       0
Bank Sta=477.69,495.21
XS Rating Curve= 0 ,0
Exp/Cntr(USF)=0,0
Exp/Cntr=0.3,0.1

Type RM Length L Ch R = 1 ,2557    ,217.2,208.2,194.9
XS GIS Cut Line= 6
2247090.06916658542680.5151016532246713.70384642 542683.59828292
2246694.96191797542653.611197398 2246673.0070875 542621.21443536
2246641.34390422542574.7924353062246345.28160142542666.845420209
#Sta/Elev= 30
       0 3011.75    93.9 2970.01   169.9 2941.88   185.9 2937.89   233.9  2929.2
   281.9 2926.84   301.9 2917.01   329.9 2913.64   480.7 2910.67   484.8 2910.08
  491.482904.412   494.9 2902.63  507.852904.415   512.5 2909.52   516.7 2911.14
   533.4 2910.79     546 2923.04   555.5 2929.28   609.4 2960.31   617.2 2962.93
   625.6 2969.49   637.7  2973.1   646.5 2979.78   676.1 2994.82   726.1 3024.34
   738.7 3032.66   751.2 3043.72   772.2 3047.33   784.7 3059.77   817.1 3078.85
#Mann= 3 ,-1,0
       0      .1       0  491.48    .045       0  507.85      .1       0
Bank Sta=491.48,507.85
XS Rating Curve= 0 ,0
Exp/Cntr(USF)=0,0
Exp/Cntr=0.3,0.1

Type RM Length L Ch R = 1 ,2349    ,386.3,393.4,398.8
XS GIS Cut Line= 4
2247096.94311121542459.2206228652246709.64451754542356.242078293
2246594.48476318 542412.541106412246286.83248265542532.096840443
#Sta/Elev= 30
       0 3000.18    25.6 2987.65    79.4 2969.63   141.5 2939.31   158.1 2936.15
   174.6 2928.68   236.7 2915.25   311.2 2908.52   327.8 2903.83     376 2901.41
   426.5 2902.24   441.4 2898.59   446.9 2897.58  460.272898.594   482.5  2901.8
   518.2 2901.38   527.1 2904.67   544.3 2919.78   561.5  2920.8   578.6 2939.49
   600.1 2949.31   630.1 2967.39     643 2971.78   651.7 2978.32   707.4 3007.52
   741.4 3026.99   758.9    3040   780.3 3043.18   793.9 3054.96     859  3092.8
#Mann= 5 ,-1,0
       0      .1       0     210     .05       0     310      .1       0
   441.4    .045       0  460.27      .1       0
#XS Ineff= 2 , 0
                          486.67         2912.41
Permanent Ineff=
       F       F
Bank Sta=441.4,460.27
XS Rating Curve= 0 ,0
Exp/Cntr=0.3,0.1

Type RM Length L Ch R = 1 ,1955    ,521.1,510.4,504.1
XS GIS Cut Line= 4
2247036.71658491542036.6619306492246604.97478067542051.731986244
 2246539.7979129 542023.419971362246240.11391455542174.942042064
#Sta/Elev= 30
       0 3034.77    44.6 3011.28   124.6 2964.18   136.4 2961.16   159.6  2949.7
   168.6 2943.05   188.7 2936.93   236.9 2903.88   252.7 2896.33   336.7 2889.12
   396.8 2890.31   412.8 2887.64   432.9 2890.81  475.732887.192   480.8 2885.96
  489.492887.192   498.3 2890.18   539.8 2891.31   551.3 2894.05   569.9 2906.52
   596.8 2928.93   619.2 2930.43   635.1  2943.8   681.9 2966.69   713.3 2985.67
   726.8 2989.86     781 3021.55   807.4 3041.57   822.6 3042.92   838.9 3056.21
#Mann= 5 ,-1,0
       0      .1       0     462     .05       0  475.73    .045       0
  489.49     .05       0  543.07      .1       0
#XS Ineff= 2 , 0
           431.7 2898.39
Permanent Ineff=
       F       F
Bank Sta=475.73,489.49
XS Rating Curve= 0 ,0
Exp/Cntr=0.3,0.1

Type RM Length L Ch R = 1 ,1445    ,549.1,544.7,541.3
XS GIS Cut Line= 4
2246659.15934521 541430.435054292246517.52164437541598.314517721
2246407.05433543 541742.205476062246155.86505968542006.229355988
#Sta/Elev= 30
       0 3022.65    24.5 3007.96    71.6 2976.22   110.1 2953.59   137.5 2934.46
   151.7 2930.29   191.4 2901.23   215.5 2880.48   223.3 2875.71   231.2 2873.91
   288.3 2875.15   329.2  2873.1   336.8 2872.33  342.75  2873.1   349.3 2874.95
   364.5 2874.65   373.8  2877.7   436.3 2879.54   463.3 2883.31   498.6 2901.31
   526.9 2918.99   544.5 2920.27   559.7 2932.18   609.4 2957.76     637 2975.12
   648.1 2978.57   696.6 3006.77     739 3034.82     756 3037.51   765.5 3047.47
#Mann= 5 ,-1,0
       0      .1       0  289.65     .05       0   329.2    .045       0
  342.75     .05       0  411.05      .1       0
#XS Ineff= 2 , 0
          289.82 2880.54
Permanent Ineff=
       F       F
Bank Sta=329.2,342.75
XS Rating Curve= 0 ,0
Exp/Cntr=0.3,0.1

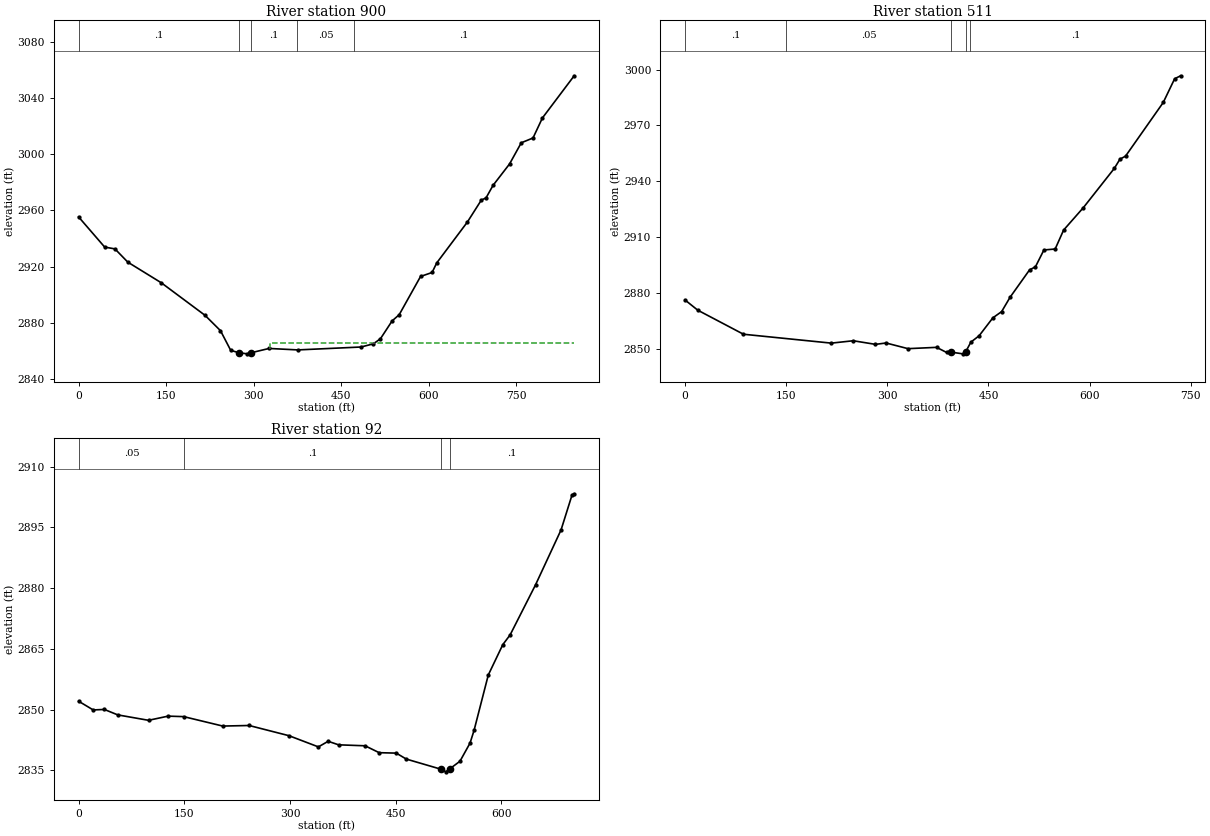
Type RM Length L Ch R = 1 ,900     ,390.8,388.9,387.9
XS GIS Cut Line= 4
2246288.65303678541232.4616846382246057.57758989541339.479261747
2246022.43527124541492.4904210062245977.57349126541927.369618773
#Sta/Elev= 30
       0 2955.37    44.6 2933.88    62.2 2932.59    84.3 2923.11   141.6 2908.41
   216.5  2885.2     243 2874.23   260.5 2860.21  274.832858.475   289.2 2857.72
  295.232858.475   326.2 2861.56   375.4 2860.52   483.6 2862.59   504.8 2864.85
   516.9 2868.45     537 2881.23   549.1 2885.64   585.7 2912.93   605.4 2915.75
   613.4 2922.59   665.9 2951.76   689.8 2967.42   697.8 2968.96   709.9 2977.95
   738.1 2993.17   758.2 3008.29   778.3 3011.71   794.4    3026   848.8 3056.09
#Mann= 5 ,-1,0
       0      .1       0  274.83    .045       0  295.23      .1       0
  374.65     .05       0  471.65      .1       0
#XS Ineff= 2 , 0
                          327.93         2865.76
Permanent Ineff=
       F       F
Bank Sta=274.83,295.23
XS Rating Curve= 0 ,0
Exp/Cntr=0.3,0.1

Type RM Length L Ch R = 1 ,511     ,420.9,419.9,417.6
XS GIS Cut Line= 4
2246000.32741686541254.8027003862245724.87925074541506.283132073
2245725.41057052541564.7283078192245813.07833414541855.360227215
#Sta/Elev= 30
       0 2876.08    18.8 2870.62    86.6 2857.68   216.9  2852.9   249.4 2854.18
   282.4 2852.24   298.1 2852.97   330.6 2849.93     373 2850.63   387.9 2847.88
   393.92848.085   411.9 2847.14   415.9 2848.07   423.9 2853.44   436.1 2856.86
   456.5 2866.51   469.5 2869.86     482 2877.57     511 2892.35   519.6 2893.93
   532.2 2903.02   548.9 2903.53   561.4 2913.71   590.7 2925.78   636.6 2946.89
     645 2951.87   653.3  2953.5   709.2 2982.36   726.1 2995.12     735 2996.72
#Mann= 5 ,-1,0
       0      .1       0     150     .05       0   393.9    .045       0
   415.9     .05       0  422.98      .1       0
Bank Sta=393.9,415.9
XS Rating Curve= 0 ,0
Exp/Cntr(USF)=0,0
Exp/Cntr=0.3,0.1

Type RM Length L Ch R = 1 ,92      ,,,
XS GIS Cut Line= 5
2245773.69801644541374.6985887372245465.33068687541555.607159294
2245340.59258034541649.6751930272245341.55910195541681.014930497
2245441.70490916541803.571069194
#Sta/Elev= 30
       0 2852.09    20.7 2849.94    36.5 2850.06    55.5 2848.72    99.2 2847.38
     127 2848.41   149.1 2848.29   204.6 2845.96     242  2846.1   298.6 2843.58
   340.3 2840.82   354.2  2842.2     369 2841.33   406.6 2841.09   426.6 2839.39
   450.9 2839.28   465.1 2837.81   513.7 2835.34   521.3 2834.66  526.55 2835.36
   541.3 2837.28   555.6 2841.76   561.3  2844.9   581.5 2858.57   602.1 2866.06
   612.5 2868.47   648.6 2880.84   684.8 2894.39   700.3 2902.97   703.4  2903.3
#Mann= 4 ,-1,0
       0     .05       0     150      .1       0   513.7    .045       0
  526.55      .1       0
Bank Sta=513.7,526.55
XS Rating Curve= 0 ,0
Exp/Cntr(USF)=0,0
Exp/Cntr=0.3,0.1
LCMann Table=0

Chan Stop Cuts=-1
Use User Specified Reach Order=0
Composite Channel Slope=5